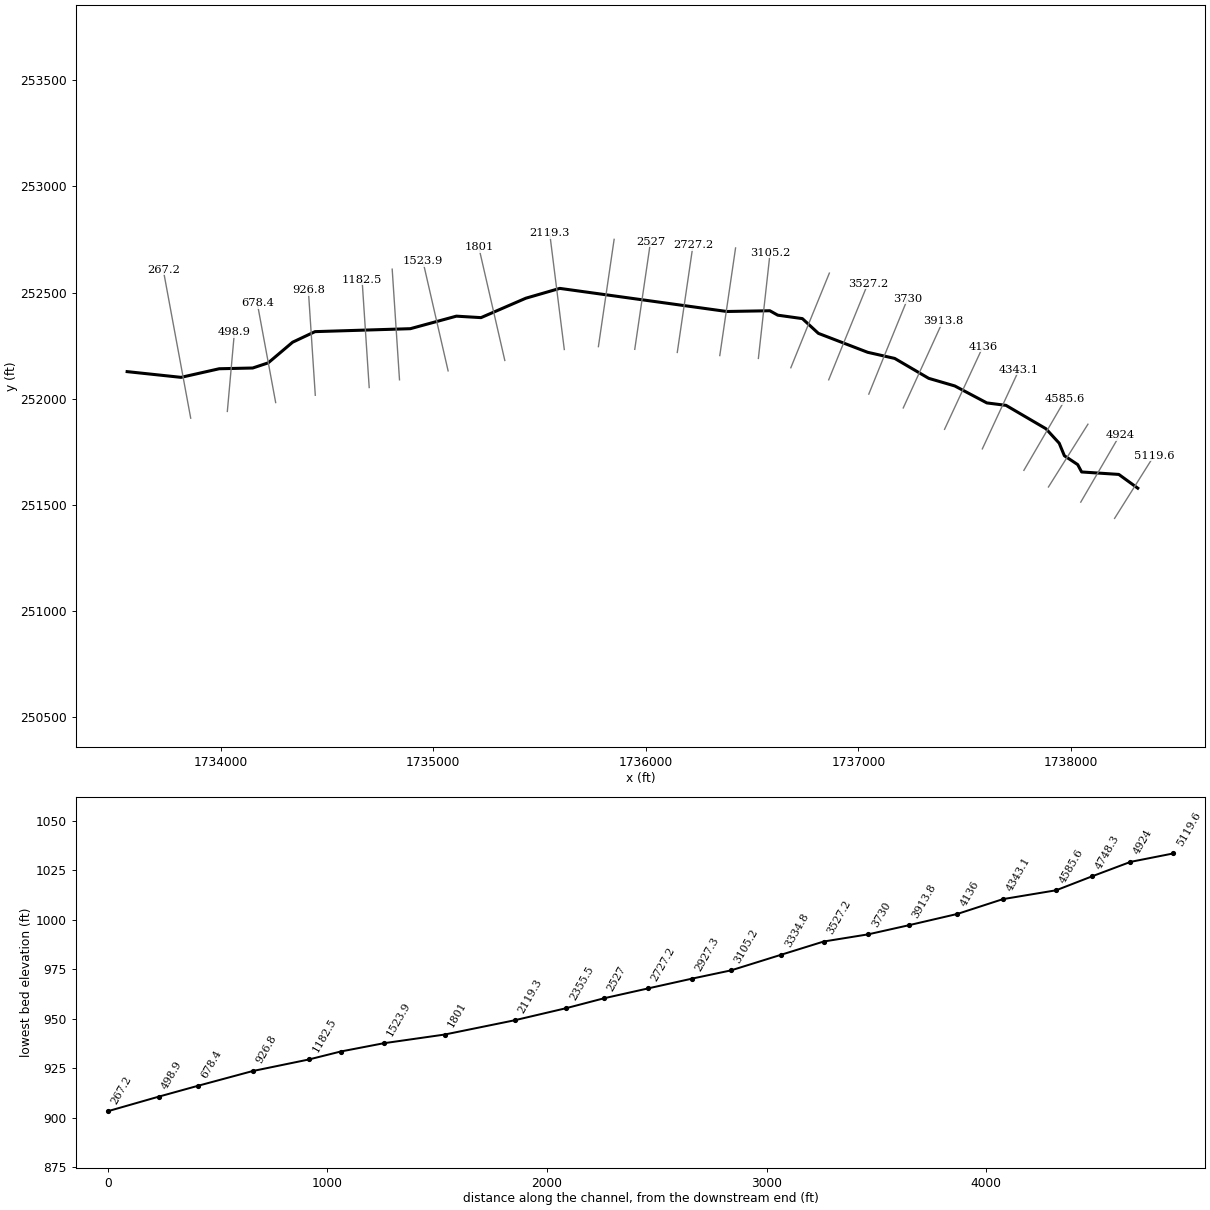
--- RIGHTELKCK.prj (project) ---

Proj Title=RIGHTELKCK
Current Plan=p01
Default Exp/Contr=0,0
English Units
Geom File=g01
Flow File=f01
Plan File=p01
BEGIN DESCRIPTION:
END DESCRIPTION:
DSS Export Rating Curves= 0
DSS Export Rating Curve Sorted= 0
DSS Export Volume Flow Curves= 0
DXF OffsetX= 0
DXF OffsetY= 0
DXF ScaleX= 0
DXF ScaleY= 0

--- RIGHTELKCK.p01 (plan) ---

Plan Title=Floodplain
Program Version=4.00
Geom File=g01
Flow File=f01
K Sum by GR=0
Std Step Tol=0.01
Critical Tol=0.01
Num of Std Step Trials=20
Max Error Tol=0.3
Flow Tol Ratio=0.001
Split Flow NTrial=30
Split Flow Tol=0.02
Split Flow Ratio=0.02
Log Output Level=0
Friction Slope Method=1
Unsteady Friction Slope Method=2
Unsteady Bridges Friction Slope Method=1
Global Log Level=0
CheckData=False
Run HTab=0
Run UNet=0
Run PostProcess=0
UNET Theta=0
UNET Theta Warmup=0
UNET ZTol=0
UNET ZSATol=0
UNET MxIter=0
UNET MaxInSteps=0
UNET DtIC=0
UNET DtMin=0
UNET MaxCRTS=0
UNET WFStab=0
UNET SFStab=0
UNET WFX=0
UNET SFX=0
UNET DSS MLevel=0
UNET DZMax Abort=0
UNET Convert EG Bridges=0
UNET Use Existing IB Tables=0
UNET Froude Limit=0
UNET Froude Power=0
Write IC File=0
Echo Input=False
Echo Output=False
Write Detailed=0

--- RIGHTELKCK.f01 (steady flow) ---

Flow Title=NFF Regression Equation
Program Version=4.00
Number of Profiles=1
Profile Names=P100yr
River Rch & RM=RIGHTELKCK,Main      ,5119.6
1071.559
River Rch & RM=RIGHTELKCK,Main      ,498.9
1154.822
River Rch & RM=RIGHTELKCK,Main      ,267.2
2698.075
Boundary for River Rch & Prof#=RIGHTELKCK,Main      ,1
Up Type=0
Dn Type=3
Dn Slope=0.028874

--- RIGHTELKCK.g01 (geometry) ---

Geom Title=USGS 10m DEM
Program Version=4.00

River Reach=RIGHTELKCK      ,Main
Reach XY= 30
     1738313.834      251577.787     1738224.652      251642.646
     1738049.763      251654.228     1738031.232      251688.974
     1737968.689       251730.67     1737944.367      251789.738
     1737881.824      251858.072     1737694.195      251968.101
     1737603.855      251979.683     1737453.288      252059.599
     1737330.519      252095.504     1737170.687      252189.318
     1737043.285      252218.273     1736811.644      252307.455
     1736736.361      252376.947      1736620.54      252393.162
     1736583.478       252414.01     1736380.793      252410.535
     1735595.531      252519.406     1735435.699      252473.078
     1735224.906       252381.58     1735109.085      252388.529
     1734892.502      252329.461     1734444.277      252315.562
      1734338.88       252265.76     1734224.218       252168.47
     1734151.251      252144.148     1733993.736      252140.674
     1733814.214      252100.137     1733560.619      252127.099

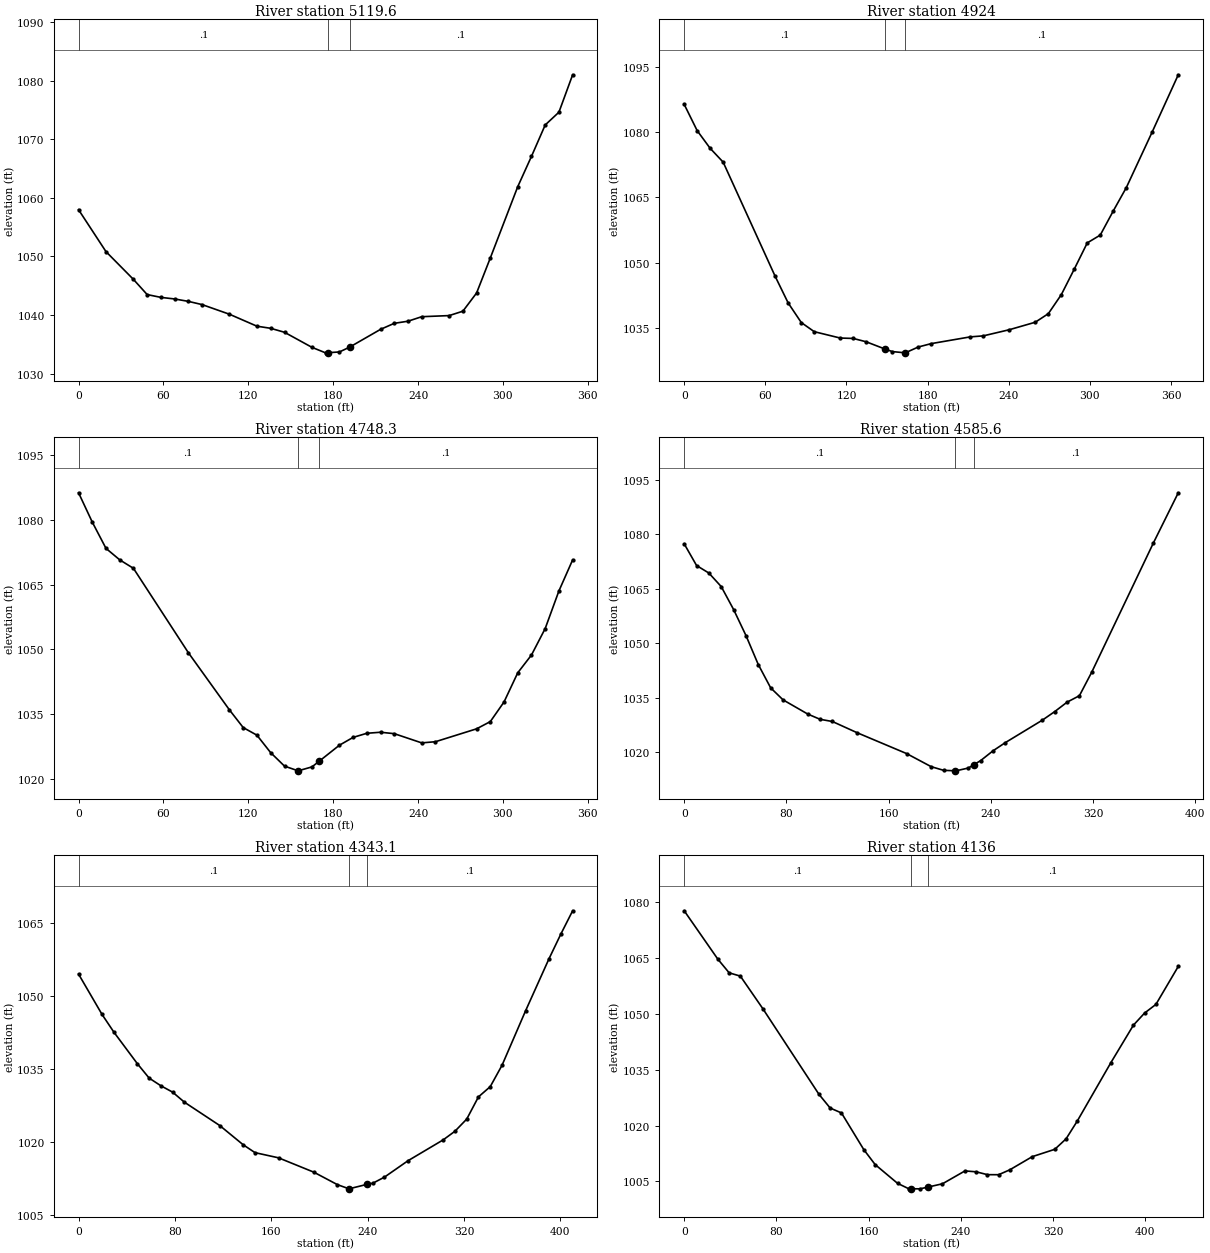
Type RM Length L Ch R = 1 ,5119.6  ,195.4,195.6,195.1
XS GIS Cut Line= 2
     1738204.807      251435.469     1738390.494      251731.336
#Sta/Elev= 30
       0 1057.98    19.4 1050.82    38.8 1046.08    48.5 1043.49    58.2 1043.01
    67.9 1042.74    77.6 1042.33    87.3 1041.78   106.7 1040.13   126.1 1038.09
   135.8 1037.73   145.6 1037.05     165 1034.48   174.6 1033.54   176.6 1033.57
   184.4 1033.69   191.6 1034.51   213.5 1037.55   223.2 1038.58   232.9 1038.94
   242.6 1039.71     262  1039.9   271.7 1040.65   281.4 1043.76   291.1 1049.74
   310.5 1061.92   320.2 1067.09   329.9 1072.45   339.6 1074.63   349.3 1081.02
#Mann= 3 , 0 , 0
       0      .1       0   176.6    .045       0   191.6      .1       0
Bank Sta=176.6,191.6
XS Rating Curve= 0 ,0
Exp/Cntr=0.3,0.1

Type RM Length L Ch R = 1 ,4924    ,176.7,175.6,174.8
XS GIS Cut Line= 2
     1738045.754      251512.106     1738229.304      251828.095
#Sta/Elev= 30
       0 1086.36     9.6 1080.32    19.2 1076.26    28.8 1073.09    67.3 1046.83
    76.9 1040.72    86.6 1036.22    96.2 1034.12   115.4 1032.66     125 1032.57
   134.6  1031.8   148.2 1030.17   153.9 1029.55   163.2 1029.27   163.5 1029.26
   173.1  1030.6   182.7 1031.38   211.6 1032.93   221.2 1033.16   240.4 1034.57
   259.6 1036.29   269.3 1038.26   278.9 1042.63   288.5 1048.51   298.1 1054.53
   307.7 1056.32   317.4 1061.91     327 1067.25   346.2 1080.08   365.4 1093.16
#Mann= 3 , 0 , 0
       0      .1       0   148.2    .045       0   163.2      .1       0
Bank Sta=148.2,163.2
XS Rating Curve= 0 ,0
Exp/Cntr=0.3,0.1

Type RM Length L Ch R = 1 ,4748.3  ,162.1,162.7,163.4
XS GIS Cut Line= 2
     1737893.757      251583.438     1738079.444      251879.305
#Sta/Elev= 30
       0  1086.2     9.7 1079.42    19.4 1073.35    29.1  1070.7    38.8 1068.74
    77.6 1049.25   106.7 1036.01   116.4 1031.94   126.1 1030.18   135.8 1026.15
   145.6 1023.03     155 1021.97   155.2 1021.94     165 1022.85     170 1024.13
   184.4 1027.86   194.1 1029.67   203.8 1030.62   213.5 1030.86   223.2 1030.53
   242.6  1028.4   252.3 1028.67   281.4 1031.65   291.1 1033.32   300.8 1037.86
   310.5  1044.6   320.2 1048.71   329.9 1054.83   339.6 1063.52   349.3 1070.69
#Mann= 3 , 0 , 0
       0      .1       0     155    .045       0     170      .1       0
Bank Sta=155,170
XS Rating Curve= 0 ,0
Exp/Cntr=0.3,0.1

Type RM Length L Ch R = 1 ,4585.6  ,240.5,242.5,244.5
XS GIS Cut Line= 2
       1737778.2      251661.843     1737972.587       251996.24
#Sta/Elev= 30
       0 1077.36     9.7 1071.39    19.3 1069.33      29  1065.6    38.7 1059.28
    48.4 1052.11      58 1044.16    67.7 1037.75    77.4 1034.45    96.7 1030.55
   106.4  1029.1     116  1028.5   135.4 1025.41   174.1 1019.68   193.4 1016.07
   203.1 1015.07   211.8 1014.95   212.7 1014.93   222.4  1015.7   226.8 1016.63
   232.1 1017.75   241.7 1020.42   251.4 1022.69   280.4 1028.87   290.1 1031.23
   299.8 1033.83   309.4 1035.59   319.1  1042.1   367.4 1077.66   386.8  1091.4
#Mann= 3 , 0 , 0
       0      .1       0   211.8    .045       0   226.8      .1       0
Bank Sta=211.8,226.8
XS Rating Curve= 0 ,0
Exp/Cntr=0.3,0.1

Type RM Length L Ch R = 1 ,4343.1  ,207.1,207.1,207.1
XS GIS Cut Line= 2
     1737582.836      251763.106     1737755.249      252135.296
#Sta/Elev= 30
       0 1054.48    19.5 1046.21    29.3 1042.59    48.8 1036.12    58.6 1033.16
    68.4 1031.58    78.1 1030.28    87.9 1028.22   117.2 1023.44   136.7 1019.49
   146.5 1017.88     166 1016.82   195.3 1013.88   214.9 1011.32   224.6 1010.46
   224.8 1010.48   239.8  1011.4   244.2  1011.6   253.9 1012.85   273.5 1016.22
   302.8 1020.51   312.5 1022.27   322.3 1024.77     332 1029.31   341.8 1031.41
   351.6  1035.8   371.1 1046.94   390.6 1057.64   400.4 1062.68   410.2 1067.46
#Mann= 3 , 0 , 0
       0      .1       0   224.8    .045       0   239.8      .1       0
Bank Sta=224.8,239.8
XS Rating Curve= 0 ,0
Exp/Cntr=0.3,0.1

Type RM Length L Ch R = 1 ,4136    ,222.1,222.2,222.3
XS GIS Cut Line= 2
     1737405.096      251855.233     1737585.224      252244.079
#Sta/Elev= 30
       0 1077.77    29.2 1064.75      39 1061.08    48.7  1060.2    68.2 1051.44
   116.9  1028.4   126.6 1024.72   136.4  1023.4   155.8 1013.52   165.6 1009.52
     185 1004.48   194.8 1003.01   196.5 1003.01   204.5 1002.99   211.5 1003.47
     224 1004.35   243.5 1007.81   253.2 1007.57     263  1006.8   272.7 1006.79
   282.4 1008.11   301.9 1011.65   321.4 1013.62   331.2 1016.44   340.9 1021.22
   370.1 1036.95   389.6 1047.01   399.3 1050.27   409.1 1052.59   428.5 1062.81
#Mann= 3 , 0 , 0
       0      .1       0   196.5    .045       0   211.5      .1       0
#XS Ineff= 2 , 0
                          246.68         1007.58
Permanent Ineff=
       F       F
Bank Sta=196.5,211.5
XS Rating Curve= 0 ,0
Exp/Cntr=0.3,0.1

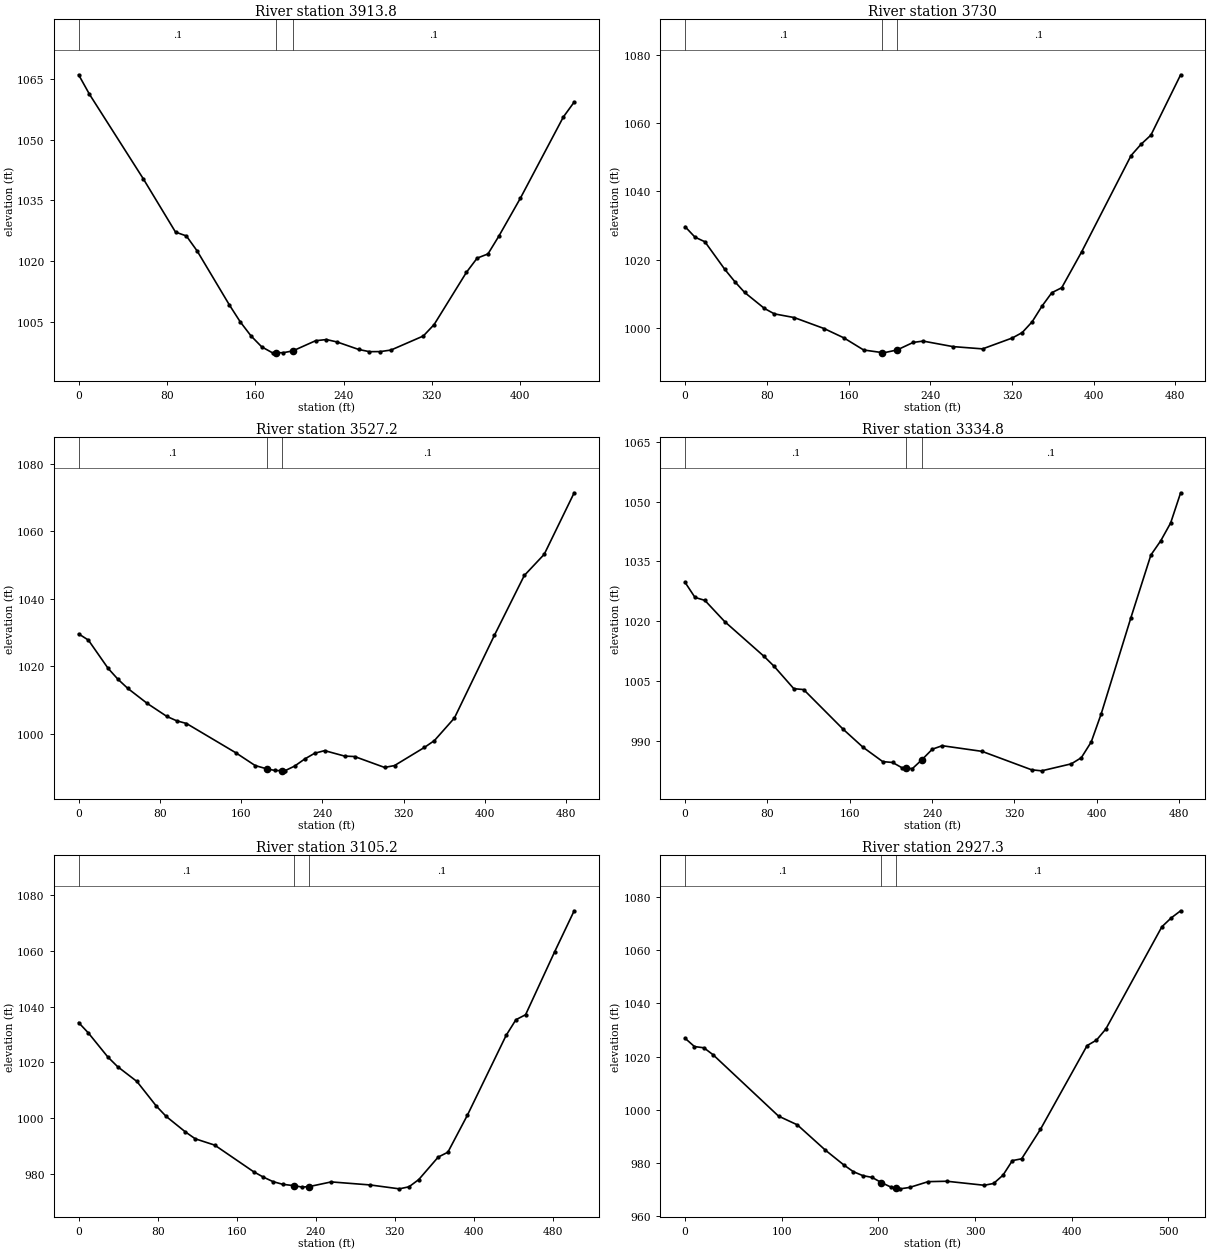
Type RM Length L Ch R = 1 ,3913.8  ,182.9,183.8,184.7
XS GIS Cut Line= 2
     1737210.812      251955.935     1737397.106      252364.439
#Sta/Elev= 30
       0 1066.13     9.8 1061.31    58.6 1040.36    87.8 1027.16    97.6 1026.22
   107.4 1022.49   136.6 1009.12   146.4 1004.95   156.2 1001.45   165.9  998.74
   175.7  997.26     179  997.27   185.4   997.3     194  997.73   214.7 1000.26
   224.5 1000.55   234.2  999.95   253.8  998.09   263.5  997.55   273.3  997.57
     283  997.95   312.3 1001.43   322.1 1004.26   351.4 1017.21   361.1 1020.72
   370.9 1021.76   380.7 1026.14   400.2 1035.53   439.2 1055.68     449 1059.37
#Mann= 3 , 0 , 0
       0      .1       0     179    .045       0     194      .1       0
#XS Ineff= 2 , 0
                          224.09         1000.53
Permanent Ineff=
       F       F
Bank Sta=179,194
XS Rating Curve= 0 ,0
Exp/Cntr=0.3,0.1

Type RM Length L Ch R = 1 ,3730    ,202.8,202.8,202.8
XS GIS Cut Line= 3
     1737048.755      252021.115      1737117.94      252192.217
     1737231.318      252470.512
#Sta/Elev= 30
       0 1029.63     9.7 1026.56    19.4 1025.21    38.8 1017.16    48.6 1013.56
    58.3 1010.37    77.7 1005.68    87.4  1004.1   106.8 1003.02     136  999.81
   155.4  997.08   174.8  993.52   192.5  992.78   194.2  992.69   207.5  993.53
   223.3  995.74     233  996.13   262.1  994.52   291.2  993.85   320.3  997.04
     330  998.62   339.7 1001.77   349.4 1006.38     359  1010.3   368.7 1011.76
   388.1 1022.21   436.6 1050.47   446.3 1053.75     456 1056.44   485.1 1074.11
#Mann= 3 , 0 , 0
       0      .1       0   192.5    .045       0   207.5      .1       0
Bank Sta=192.5,207.5
XS Rating Curve= 0 ,0
Exp/Cntr=0.3,0.1

Type RM Length L Ch R = 1 ,3527.2  ,191.8,192.3,192.9
XS GIS Cut Line= 3
     1736860.246       252088.44     1736932.623      252267.433
     1737043.873      252540.504
#Sta/Elev= 30
       0 1029.65     9.6 1027.81      29 1019.44    38.6 1016.24    48.3 1013.52
    67.6 1009.03    86.9 1005.18    96.5  1003.9   106.2 1003.09   154.5  994.46
   173.8  990.63   185.6  989.62   193.1  989.18   200.6  989.09   202.9  989.06
   212.7  990.47   222.6  992.57   232.4  994.27   242.2  995.05   261.9  993.43
   271.7   993.3   301.2  990.07     311  990.62   340.5  996.01   350.3  998.03
     370 1004.72   409.3 1029.19   438.8 1046.96   458.4 1053.23   487.9 1071.47
#Mann= 3 , 0 , 0
       0      .1       0   185.6    .045       0   200.6      .1       0
Bank Sta=185.6,200.6
XS Rating Curve= 0 ,0
Exp/Cntr=0.3,0.1

Type RM Length L Ch R = 1 ,3334.8  ,224.4,229.6,234.9
XS GIS Cut Line= 3
     1736682.141       252145.36     1736757.709      252332.245
     1736863.322      252591.479
#Sta/Elev= 30
       0 1029.74     9.6 1025.97    19.2 1025.23    38.4 1019.92    76.8 1011.15
    86.4  1008.7   105.6 1003.06   115.2 1002.83   153.6  992.87   172.8  988.37
     192  984.75   201.6  984.53   211.2  983.14   214.8  983.09   220.9     983
   229.8  985.14   240.2  987.86   249.8  988.74   288.5  987.32   336.7  982.69
   346.4  982.43   375.3  984.19     385  985.73   394.6  989.67   404.3  996.73
   433.2  1020.9   452.6 1036.62   462.2  1040.2   471.8 1044.67   481.5 1052.24
#Mann= 3 , 0 , 0
       0      .1       0   214.8    .045       0   229.8      .1       0
Bank Sta=214.8,229.8
XS Rating Curve= 0 ,0
Exp/Cntr=0.3,0.1

Type RM Length L Ch R = 1 ,3105.2  ,178.6,177.9,177.2
XS GIS Cut Line= 2
      1736529.48      252189.349     1736584.642      252688.114
#Sta/Elev= 30
       0 1034.23     9.8 1030.53    29.5  1021.9    39.4 1018.42      59 1013.08
    78.7 1004.22    88.6 1000.53   108.2  994.92   118.1  992.47   137.8   990.2
   177.1  980.66     187  978.71   196.8  977.09   206.6  976.12   218.5  975.61
   226.3  975.12   233.5   975.3   255.8  976.98   295.2  975.89   324.7  974.49
   334.5  975.22   344.4  977.81   364.1   985.9   373.9  987.65   393.6  1000.9
   432.9 1029.63   442.8 1035.26   452.6 1037.06   482.1 1059.73   501.8 1074.41
#Mann= 3 , 0 , 0
       0      .1       0   218.5    .045       0   233.5      .1       0
Bank Sta=218.5,233.5
XS Rating Curve= 0 ,0
Exp/Cntr=0.3,0.1

Type RM Length L Ch R = 1 ,2927.3  ,200.1,200.1,200.1
XS GIS Cut Line= 2
     1736347.983      252202.748     1736422.215      252710.002
#Sta/Elev= 30
       0 1026.84     9.7 1023.74    19.4 1023.28      29 1020.65    96.7  997.62
   116.1  994.35   145.1  984.86   164.4  979.24   174.1  976.76   183.8  975.29
   193.5  974.61   202.9   972.7   212.8     971   217.9  970.64   222.5  970.32
   232.2  970.84   251.5  973.02   270.8  973.17   309.5  971.66   319.2  972.34
   328.9  975.45   338.6  980.92   348.2   981.6   367.6  992.63   415.9  1024.1
   425.6 1026.15   435.3 1030.33   493.3 1068.72     503 1072.06   512.7 1074.72
#Mann= 3 , 0 , 0
       0      .1       0   202.9    .045       0   217.9      .1       0
Bank Sta=202.9,217.9
XS Rating Curve= 0 ,0
Exp/Cntr=0.3,0.1

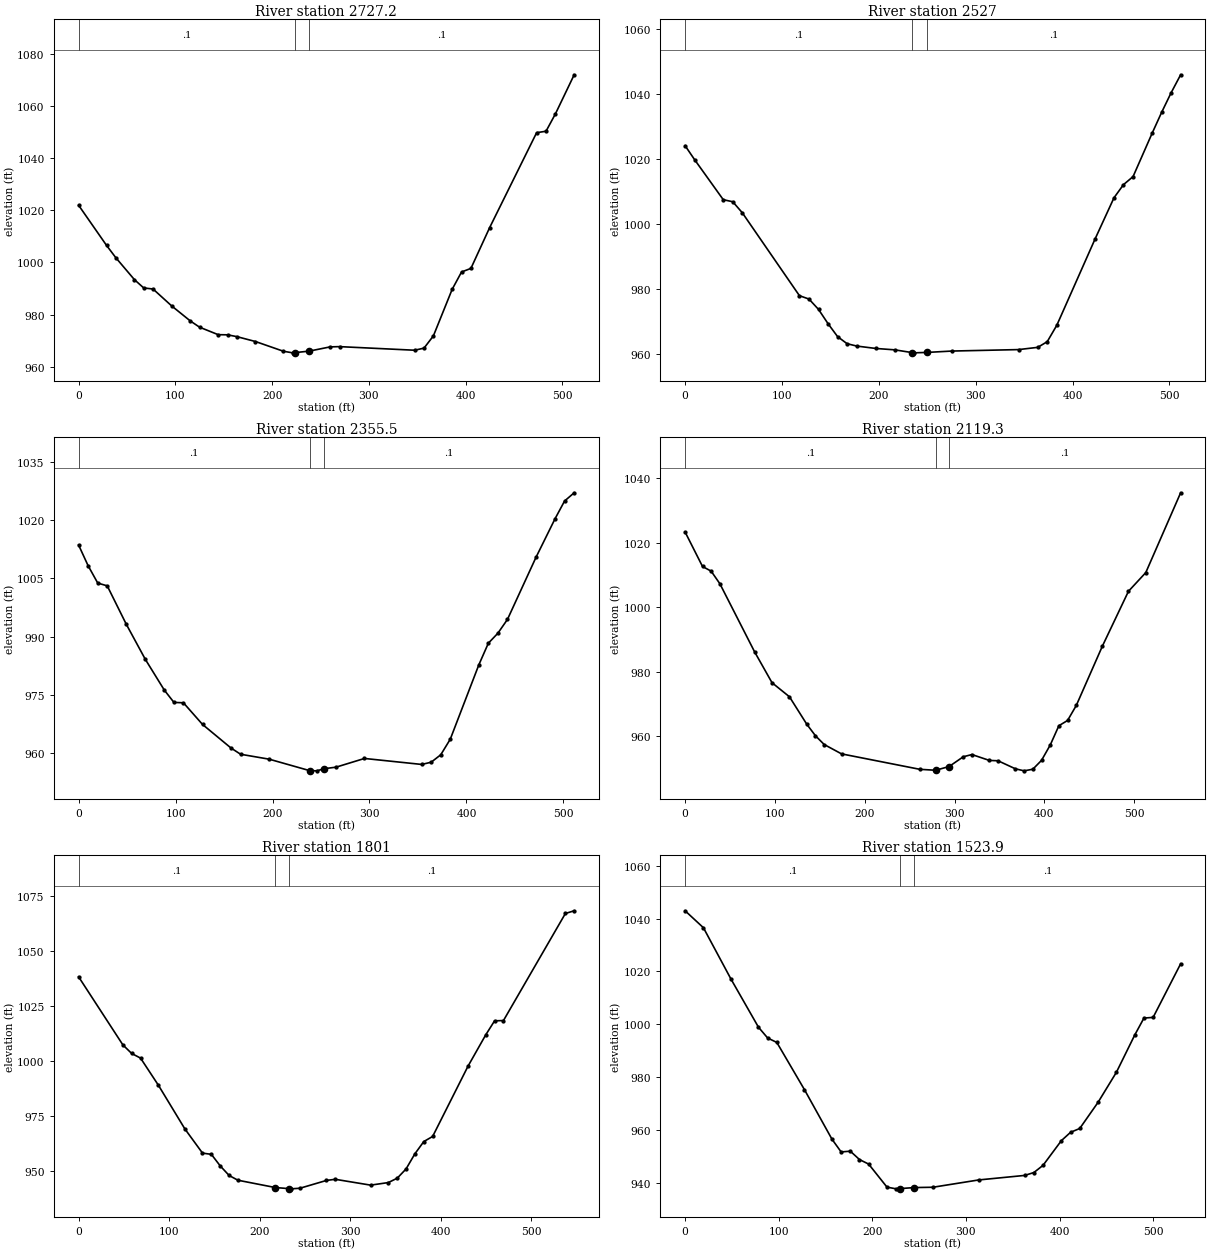
Type RM Length L Ch R = 1 ,2727.2  ,200.2,200.2,200.2
XS GIS Cut Line= 3
     1736148.013      252217.511     1736181.431      252445.868
     1736222.164      252724.213
#Sta/Elev= 30
       0  1021.9    28.8 1006.56    38.5 1001.79    57.7   993.4    67.3  990.23
    76.9  989.83    96.2  983.34   115.4   977.6     125   975.2   144.2  972.34
   153.9  972.28   163.5  971.59   182.7  969.72   211.6  965.99   221.2  965.38
   223.3  965.45   238.3  966.04   259.9  967.66   269.6  967.76   347.2  966.38
   356.9  967.18   366.6  971.86     386   989.7   395.7  996.35   405.4  997.73
   424.8 1013.39   473.3 1049.72     483 1050.27   492.7 1056.91   512.1  1071.9
#Mann= 3 , 0 , 0
       0      .1       0   223.3    .045       0   238.3      .1       0
Bank Sta=223.3,238.3
XS Rating Curve= 0 ,0
Exp/Cntr=0.3,0.1

Type RM Length L Ch R = 1 ,2527    ,171.5,171.5,171.5
XS GIS Cut Line= 2
     1735948.043      252232.274     1736022.114      252738.425
#Sta/Elev= 30
       0 1024.14     9.8 1019.84    39.4 1007.52    49.2 1006.89      59 1003.52
     118     978   127.9  976.95   137.7  973.78   147.6  969.36   157.4   965.4
   167.2  963.22   177.1   962.5   196.8  961.76   216.4  961.33   234.7  960.47
   236.1  960.41   249.7  960.54   275.4  960.96   344.3  961.41     364   962.1
   373.8  963.84   383.7   968.9     423  995.32   442.7 1008.11   452.5 1012.15
   462.4 1014.63     482 1027.92   491.9  1034.4   501.7 1040.43   511.5 1045.95
#Mann= 3 , 0 , 0
       0      .1       0   234.7    .045       0   249.7      .1       0
Bank Sta=234.7,249.7
XS Rating Curve= 0 ,0
Exp/Cntr=0.3,0.1

Type RM Length L Ch R = 1 ,2355.5  ,230.1,236.1,242.2
XS GIS Cut Line= 2
      1735777.06      252244.897     1735851.061      252750.576
#Sta/Elev= 30
       0 1013.59     9.8 1008.27    19.7 1003.81    29.5 1003.09    49.1  993.22
    68.8  984.15    88.4  976.22    98.3  973.06   108.1  972.96   127.8  967.38
   157.2   961.3   167.1   959.7   196.6  958.43   238.3  955.48   245.7  955.43
   253.3  955.99   265.4  956.37   294.8  958.62   353.8  957.08   363.6  957.65
   373.5  959.57   383.3  963.58   412.8  982.76   422.6  988.32   432.4  990.88
   442.3  994.45   471.8 1010.48   491.4 1020.39   501.2 1024.95   511.1 1027.07
#Mann= 3 , 0 , 0
       0      .1       0   238.3    .045       0   253.3      .1       0
Bank Sta=238.3,253.3
XS Rating Curve= 0 ,0
Exp/Cntr=0.3,0.1

Type RM Length L Ch R = 1 ,2119.3  ,316,318.3,320.6
XS GIS Cut Line= 2
     1735616.647      252231.401     1735548.062      252778.883
#Sta/Elev= 30
       0 1023.34    19.4 1012.65      29  1011.2    38.7 1007.31    77.4  986.18
    96.8  976.61   116.2  972.25   135.5  963.74   145.2  960.15   154.9  957.45
   174.2  954.55   261.4  949.76     279  949.47     294  950.63   309.8  953.66
   319.4  954.34   338.8  952.52   348.5  952.41   367.8  949.92   377.5  949.29
   387.2  949.79   396.9  952.54   406.6   957.3   416.2  963.27   425.9  964.91
   435.6  969.56   464.6  987.92   493.7 1004.96     513 1010.76   551.8  1035.5
#Mann= 3 , 0 , 0
       0      .1       0     279    .045       0     294      .1       0
Bank Sta=279,294
XS Rating Curve= 0 ,0
Exp/Cntr=0.3,0.1

Type RM Length L Ch R = 1 ,1801    ,277.2,277.1,277.1
XS GIS Cut Line= 2
     1735336.893      252179.715     1735214.562      252713.213
#Sta/Elev= 30
       0 1038.29    48.9  1007.4    58.6 1003.52    68.4 1001.41      88  989.17
   117.3  969.31   136.8  958.31   146.6  957.74   156.4  952.49   166.2  948.16
   175.9     946   217.1  942.69   232.1  942.19   234.6  942.09   244.4  942.36
   273.7   945.9   283.4  946.42   322.5  943.77   342.1  944.94   351.9  946.94
   361.6   951.1   371.4     958   381.2  963.54     391  965.87   430.1  997.79
   449.6 1011.95   459.4 1018.34   469.2 1018.46   537.6 1067.05   547.3 1068.28
#Mann= 3 , 0 , 0
       0      .1       0   217.1    .045       0   232.1      .1       0
Bank Sta=217.1,232.1
XS Rating Curve= 0 ,0
Exp/Cntr=0.3,0.1

Type RM Length L Ch R = 1 ,1523.9  ,199.9,196.3,192.8
XS GIS Cut Line= 2
     1735070.223      252130.634     1734951.896      252646.671
#Sta/Elev= 30
       0 1042.99    19.6 1036.56      49 1017.14    78.4   998.9    88.2  994.82
      98  993.14   127.5  975.27   156.9  956.51   166.7  951.68   176.5  951.97
   186.3   948.8   196.1  947.08   215.7  938.35   225.5  937.71   229.7   937.8
   244.7  938.19   264.7  938.31   313.7  941.08   362.8  942.79   372.6  943.88
   382.4  946.61     402  955.96   411.8  959.11   421.6  960.56   441.2  970.48
   460.8  981.86   480.4  995.97   490.2 1002.37     500 1002.62   529.4 1022.91
#Mann= 3 , 0 , 0
       0      .1       0   229.7    .045       0   244.7      .1       0
Bank Sta=229.7,244.7
XS Rating Curve= 0 ,0
Exp/Cntr=0.3,0.1

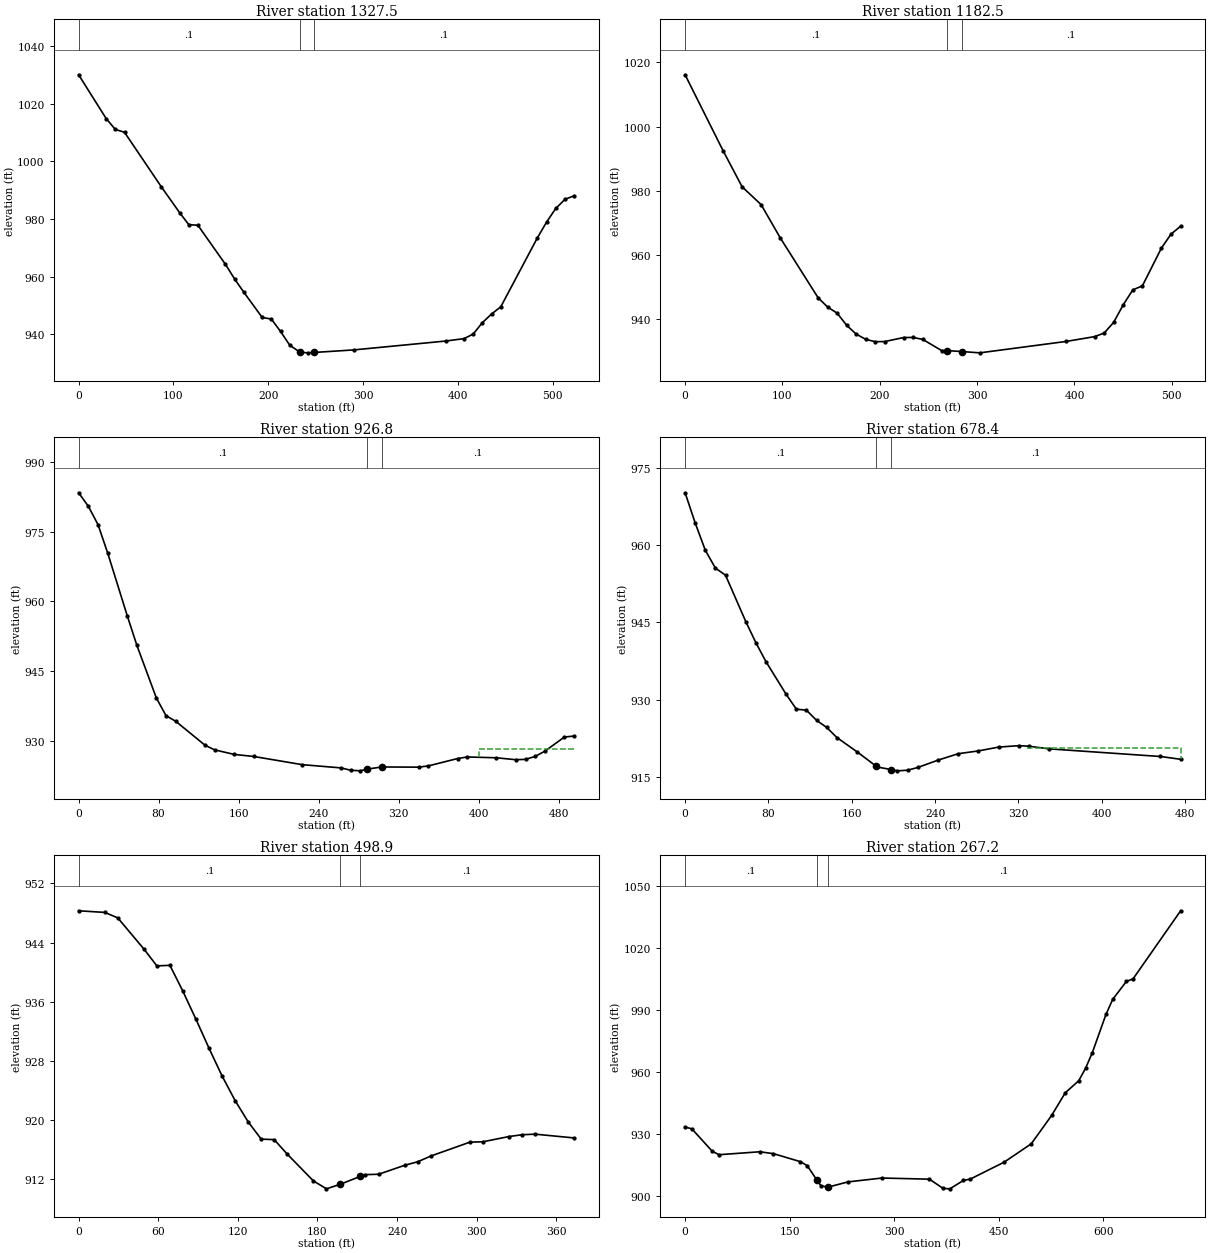
Type RM Length L Ch R = 1 ,1327.5  ,145,145,145
XS GIS Cut Line= 2
     1734841.601      252088.556     1734807.219      252610.019
#Sta/Elev= 30
       0 1030.11      29 1014.92    38.7 1011.12    48.4 1010.13    87.1  991.24
   106.4  982.26   116.1  978.08   125.8  977.82   154.8  964.28   164.5  959.17
   174.2  954.58   193.6   945.8   203.2  945.27   212.9  940.97   222.6   936.2
   233.3  933.75   241.9  933.52   248.3  933.65   290.3  934.54   387.1  937.62
   406.5  938.46   416.1  940.05   425.8     944   435.5  947.02   445.2  949.51
   483.9  973.53   493.6  978.99   503.2  983.69   512.9  986.85   522.6  988.08
#Mann= 3 , 0 , 0
       0      .1       0   233.3    .045       0   248.3      .1       0
Bank Sta=233.3,248.3
XS Rating Curve= 0 ,0
Exp/Cntr=0.3,0.1

Type RM Length L Ch R = 1 ,1182.5  ,255.8,255.7,255.7
XS GIS Cut Line= 3
     1734699.057      252052.109     1734681.072      252324.895
     1734665.565      252560.077
#Sta/Elev= 30
       0 1016.13      39  992.49    58.6  981.22    78.1  975.68    97.6   965.4
   136.7  946.64   146.4  943.78   156.2  941.86     166  938.08   175.7  935.35
   185.5  933.72   195.3  932.97     205  933.01   224.6  934.27   234.3  934.29
   244.1  933.69   263.6   930.2   269.3   930.2   284.3   929.9   302.8   929.5
   391.2  933.04   420.7  934.55   430.5  935.66   440.3     939   450.2  944.51
     460  949.13   469.8  950.37   489.4  962.16   499.2  966.49   509.1  968.94
#Mann= 3 , 0 , 0
       0      .1       0   269.3    .045       0   284.3      .1       0
Bank Sta=269.3,284.3
XS Rating Curve= 0 ,0
Exp/Cntr=0.3,0.1

Type RM Length L Ch R = 1 ,926.8   ,245.9,248.3,249.9
XS GIS Cut Line= 2
     1734445.538      252015.662     1734412.936      252510.134
#Sta/Elev= 30
       0  983.33     9.7  980.44    19.4  976.49    29.2  970.31    48.6  956.95
    58.3  950.56    77.7  939.31    87.4   935.5    97.2  934.28   126.3  929.17
     136  928.16   155.5  927.19   174.9  926.75   223.5  924.99   262.4  924.29
   272.1  923.79   281.8  923.66   288.3  924.02   303.3  924.49   340.1  924.45
   349.8  924.72     379   926.3   388.7  926.64   417.8  926.46   437.2  926.05
     447  926.12   456.7  926.77   466.4  927.89   485.8  930.91   495.6  931.13
#Mann= 3 , 0 , 0
       0      .1       0   288.3    .045       0   303.3      .1       0
#XS Ineff= 2 , 0
                          400.35          928.29
Permanent Ineff=
       F       F
Bank Sta=288.3,303.3
XS Rating Curve= 0 ,0
Exp/Cntr=0.3,0.1

Type RM Length L Ch R = 1 ,678.4   ,185.4,179.5,174.5
XS GIS Cut Line= 2
     1734259.179      251981.362     1734172.743      252449.285
#Sta/Elev= 30
       0  970.13     9.7  964.28    19.4  958.99    29.1  955.53    38.8  954.16
    58.3  945.16      68  941.06    77.7  937.38    97.1  931.05   106.8   928.2
   116.5  927.99   126.2  926.03     136  924.64   145.7   922.7   165.1  919.93
   183.1  917.19   184.5  916.98   198.1  916.48   203.9  916.24   213.6  916.36
   223.4  916.89   242.8  918.31   262.2  919.56   281.6   920.1     301  920.84
   320.5  921.12   330.2  921.01   349.6   920.5   456.4  919.02   475.8  918.48
#Mann= 3 , 0 , 0
       0      .1       0   183.1    .045       0   198.1      .1       0
#XS Ineff= 2 , 0
                          328.68          920.63
Permanent Ineff=
       F       F
Bank Sta=183.1,198.1
XS Rating Curve= 0 ,0
Exp/Cntr=0.3,0.1

Type RM Length L Ch R = 1 ,498.9   ,225.6,231.7,237.9
XS GIS Cut Line= 2
      1734031.86      251939.524     1734065.126      252311.571
#Sta/Elev= 30
       0  948.31    19.7  948.09    29.5  947.35    49.2  943.14      59  940.86
    68.8  940.94    78.6  937.43    88.5  933.62    98.3  929.72   108.1  925.99
     118  922.64   127.8  919.78   137.6  917.45   147.4  917.38   157.3  915.41
   176.9  911.81   186.8  910.73   197.1  911.34   212.1   912.4   216.2  912.65
   226.1   912.7   245.7  913.91   255.6  914.39   265.4  915.16   294.9  917.04
   304.7  917.09   324.4   917.8   334.2  918.04     344  918.12   373.5  917.61
#Mann= 3 , 0 , 0
       0      .1       0   197.1    .045       0   212.1      .1       0
Bank Sta=197.1,212.1
XS Rating Curve= 0 ,0
Exp/Cntr=0.3,0.1

Type RM Length L Ch R = 1 ,267.2   ,271.6,267.2,262.8
XS GIS Cut Line= 2
     1733859.576      251907.816     1733730.482      252606.675
#Sta/Elev= 30
       0  933.34     9.7  932.47    38.9   921.6    48.7  919.93   107.1  921.35
   126.6  920.44   165.5  916.54   175.2   914.6   189.3  907.49   194.7  904.95
   204.3  904.15   233.6  906.74   282.3  908.62   350.5  908.07   369.9   903.6
   379.7  903.38   399.2  907.46   408.9  908.09   457.6  916.32   496.5  925.22
   525.7  938.98   545.2  949.92   564.6   955.8   574.4  961.85   584.1  969.45
   603.6  987.93   613.3  995.24   632.8  1003.9   642.5  1005.2   710.7 1038.18
#Mann= 3 , 0 , 0
       0      .1       0   189.3    .045       0   204.3      .1       0
Bank Sta=189.3,204.3
XS Rating Curve= 0 ,0
Exp/Cntr=0.3,0.1

Chan Stop Cuts=-1
Use User Specified Reach Order=0